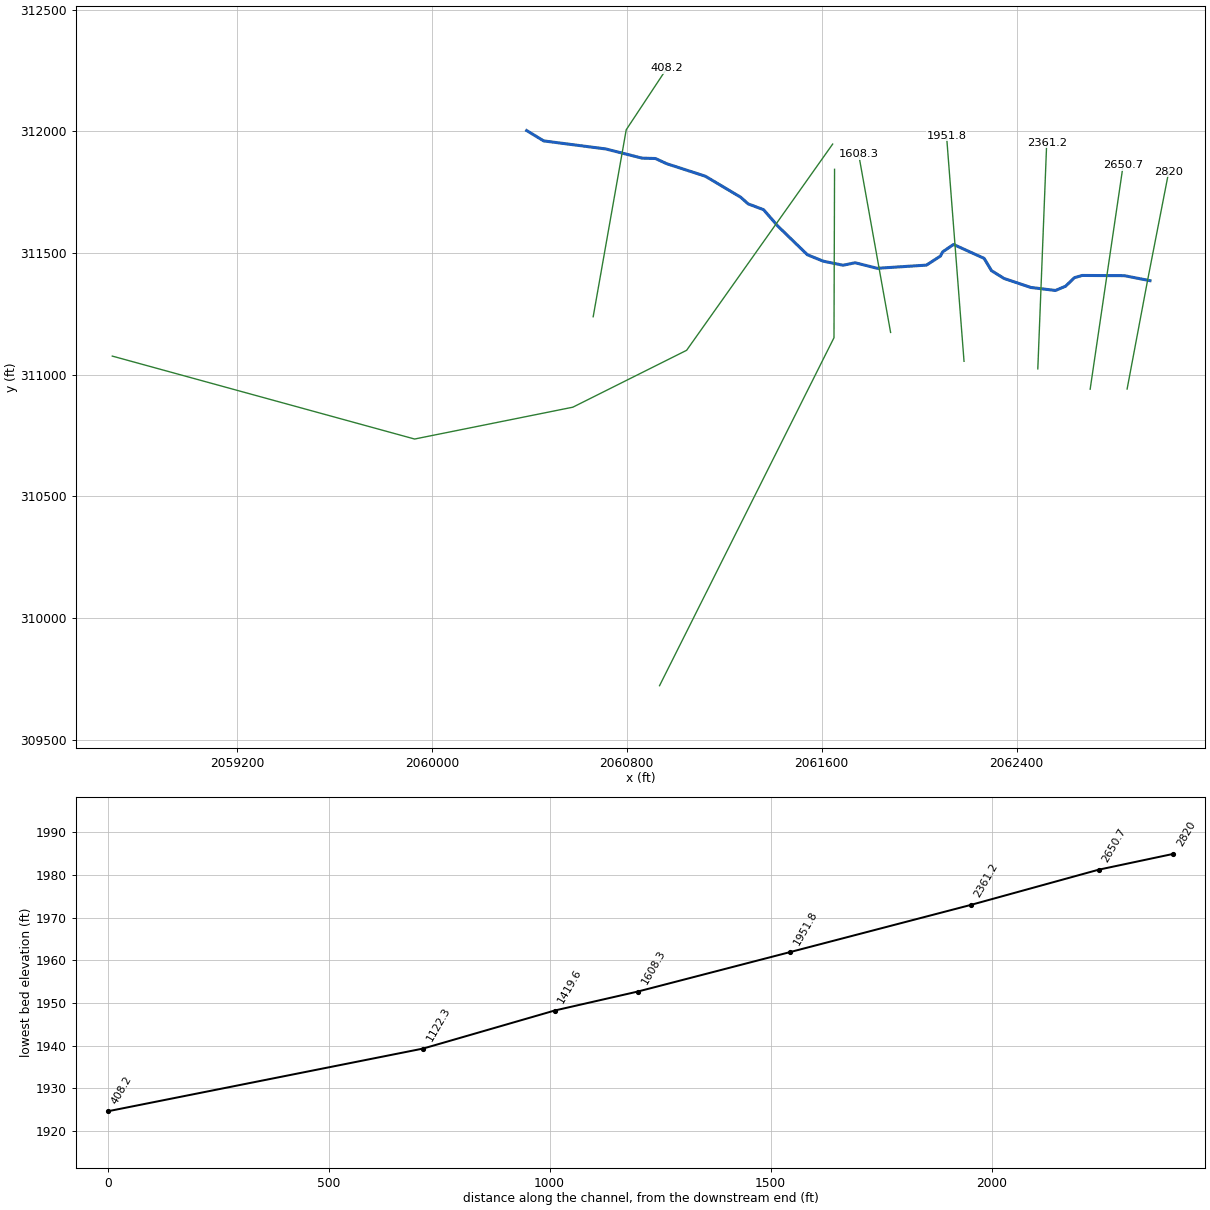
--- NP56.prj (project) ---

Proj Title=NP56
Current Plan=p01
Default Exp/Contr=0,0
English Units
Geom File=g01
Flow File=f01
Plan File=p01
BEGIN DESCRIPTION:
END DESCRIPTION:
DSS Export Rating Curves= 0
DSS Export Rating Curve Sorted= 0
DSS Export Volume Flow Curves= 0
DXF OffsetX= 0
DXF OffsetY= 0
DXF ScaleX= 0
DXF ScaleY= 0

--- NP56.p01 (plan) ---

Plan Title=Floodplain
Program Version=4.00
Geom File=g01
Flow File=f01
K Sum by GR=0
Std Step Tol=0.01
Critical Tol=0.01
Num of Std Step Trials=20
Max Error Tol=0.3
Flow Tol Ratio=0.001
Split Flow NTrial=30
Split Flow Tol=0.02
Split Flow Ratio=0.02
Log Output Level=0
Friction Slope Method=1
Unsteady Friction Slope Method=2
Unsteady Bridges Friction Slope Method=1
Global Log Level=0
CheckData=False
Run HTab=0
Run UNet=0
Run PostProcess=0
UNET Theta=0
UNET Theta Warmup=0
UNET ZTol=0
UNET ZSATol=0
UNET MxIter=0
UNET MaxInSteps=0
UNET DtIC=0
UNET DtMin=0
UNET MaxCRTS=0
UNET WFStab=0
UNET SFStab=0
UNET WFX=0
UNET SFX=0
UNET DSS MLevel=0
UNET DZMax Abort=0
UNET Convert EG Bridges=0
UNET Use Existing IB Tables=0
UNET Froude Limit=0
UNET Froude Power=0
Write IC File=0
Echo Input=False
Echo Output=False
Write Detailed=0

--- NP56.f01 (steady flow) ---

Flow Title=NFF Regression Equation
Program Version=4.00
Number of Profiles=1
Profile Names=P100yr
River Rch & RM=NP56,Main      ,2820
    1106
River Rch & RM=NP56,Main      ,1122.3
    1134
Boundary for River Rch & Prof#=NP56,Main      ,1
Up Type=0
Dn Type=3
Dn Slope=0.023407

--- NP56.g01 (geometry) ---

Geom Title=USGS 10m DEM
Program Version=4.00

River Reach=NP56            ,Main
Reach XY= 30
     2062947.146      311385.943     2062841.549      311406.494
     2062668.903       311407.38      2062637.13      311398.164
     2062600.569      311363.103     2062559.346      311345.732
     2062458.426      311357.998     2062348.219       311395.02
     2062296.715      311427.008     2062266.427      311477.636
     2062141.073      311534.691     2062096.294      311504.363
     2062087.398      311487.111     2062029.656      311449.836
     2061827.577       311436.82     2061737.237      311459.629
     2061687.881      311449.312     2061605.764      311466.169
     2061541.295      311492.371     2061419.748      311610.442
     2061361.386      311677.698     2061298.111      311701.524
     2061267.722      311728.707     2061122.544      311815.186
      2060964.27      311866.509     2060917.358      311887.953
     2060863.361      311889.406     2060714.049      311927.208
     2060459.379      311960.234     2060389.117      312002.904

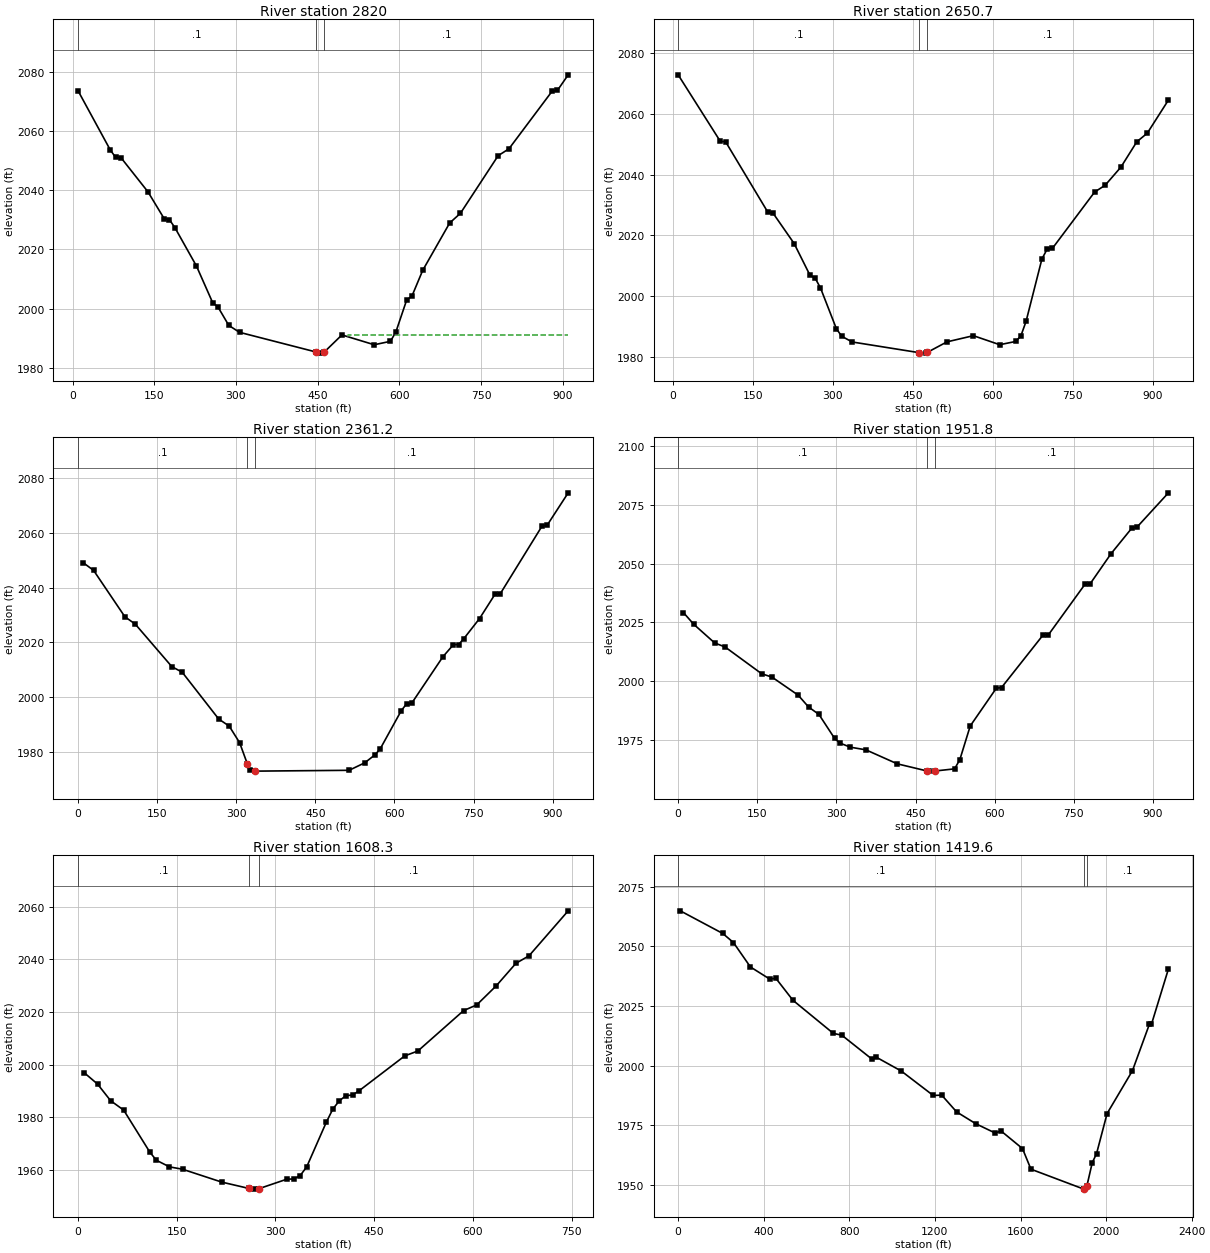
Type RM Length L Ch R = 1 ,2820    ,168.3,169.2,170.3
XS GIS Cut Line= 3
      2062853.24       310940.68      2062937.33      311387.854
     2063024.251      311834.472
#Sta/Elev= 30
     9.9 2073.69    69.2 2053.65    79.1  2051.1      89 2050.99   138.5 2039.46
   168.2 2030.41     178 2030.03   187.9 2027.38   227.5  2014.4   257.2 2002.05
   267.1 2000.53   286.9 1994.33   306.6    1992   447.5 1985.33     455 1984.97
   462.5  1985.4   494.6 1991.12   553.9  1987.8   583.6 1988.96   593.5 1992.05
   613.3 2002.84   623.2 2004.28   642.9 2012.94   692.4 2028.94   712.2 2032.23
   781.4 2051.68   801.2    2054   880.3 2073.43   890.2 2073.73     910    2079
#Mann= 3 , 0 , 0
     9.9      .1       0   447.5    .045       0   462.5      .1       0
#XS Ineff= 2 , 0
                          504.87         1991.04
Permanent Ineff=
       F       F
Bank Sta=447.5,462.5
XS Rating Curve= 0 ,0
Exp/Cntr=0.3,0.1

Type RM Length L Ch R = 1 ,2650.7  ,287.1,289.5,291.9
XS GIS Cut Line= 2
     2062701.611      310939.993     2062836.846      311859.476
#Sta/Elev= 30
     9.9 2072.83      89 2050.93    98.9 2050.81     178 2027.66   187.9 2027.31
   227.4 2017.33   257.1  2006.9   266.9  2005.9   276.8 2002.73   306.5 1989.36
   316.4 1986.84   336.2 1984.93     462 1981.41   474.6 1981.26     477 1981.49
   514.1 1984.97   563.6    1987     613 1984.03   642.7 1985.09   652.5 1986.85
   662.4 1991.71   692.1 2012.22     702 2015.51   711.9 2015.75     791 2034.27
   810.7 2036.49   840.4 2042.49   870.1  2050.8   889.8 2053.64   929.4 2064.53
#Mann= 3 , 0 , 0
     9.9      .1       0     462    .045       0     477      .1       0
#XS Ineff= 2 , 0
                          563.33         1986.85
Permanent Ineff=
       F       F
Bank Sta=462,477
XS Rating Curve= 0 ,0
Exp/Cntr=0.3,0.1

Type RM Length L Ch R = 1 ,2361.2  ,405.7,409.3,413
XS GIS Cut Line= 2
     2062486.793      311023.471     2062523.271       311952.13
#Sta/Elev= 30
     9.9 2049.12    29.7  2046.3      89 2029.37   108.8 2026.65     178 2011.16
   197.7 2009.11   266.9 1992.02   286.7 1989.45   306.5  1983.4   320.9 1975.78
   326.3 1973.46   335.9 1973.01   336.2    1973   514.1  1973.3   543.8 1976.05
   563.6 1979.02   573.4 1981.26     613 1995.09   622.9 1997.55   632.8 1997.81
   692.1 2014.82   711.9 2019.19   721.7 2019.23   731.6 2021.39   761.3  2028.7
     791 2037.69   800.8 2037.82   879.9 2062.51   889.8 2062.88   929.4 2074.62
#Mann= 3 , 0 , 0
       0      .1       0   320.9    .045       0   335.9      .1       0
Bank Sta=320.9,335.9
XS Rating Curve= 0 ,0
Exp/Cntr=0.3,0.1

Type RM Length L Ch R = 1 ,1951.8  ,340.2,343.6,346.6
XS GIS Cut Line= 2
     2062184.022      311054.628     2062112.246      311981.227
#Sta/Elev= 30
     9.9  2029.2    29.7 2024.19    69.2 2016.31      89 2014.59   158.2 2003.26
     178  2001.8   227.4 1994.18   247.2 1989.15   266.9 1985.98   296.6 1975.81
   306.5 1973.86   326.3  1972.1   355.9 1970.97   415.3 1965.04   471.7 1962.01
   474.6 1961.94   486.7 1961.99     524  1962.9   533.9 1966.76   553.7  1981.1
   603.1  1997.1     613 1997.39   692.1 2019.77     702 2019.79   771.2 2041.19
   781.1 2041.42   820.6 2054.16   860.2 2065.06   870.1  2065.5   929.4 2079.98
#Mann= 3 , 0 , 0
       0      .1       0   471.7    .045       0   486.7      .1       0
Bank Sta=471.7,486.7
XS Rating Curve= 0 ,0
Exp/Cntr=0.3,0.1

Type RM Length L Ch R = 1 ,1608.3  ,192.6,188.6,184.6
XS GIS Cut Line= 2
      2061882.69       311173.22     2061751.396      311906.508
#Sta/Elev= 30
     9.9 1996.87    29.8 1992.64    49.7 1986.31    69.5 1982.75   109.3 1966.75
   119.2 1963.69   139.1 1961.18   158.9 1960.28   218.5 1955.39     260 1952.97
   268.2 1952.72     275 1952.89   317.8 1956.53   327.8 1956.55   337.7 1957.88
   347.6 1961.18   377.4 1978.15   387.4  1983.2   397.3  1986.3   407.2 1988.25
   417.2 1988.47   427.1 1990.08   496.6 2003.35   516.5  2005.2     586 2020.56
   605.9 2022.71   635.7    2030   665.5 2038.52   685.4 2041.38   744.9 2058.46
#Mann= 3 , 0 , 0
       0      .1       0     260    .045       0     275      .1       0
Bank Sta=260,275
XS Rating Curve= 0 ,0
Exp/Cntr=0.3,0.1

Type RM Length L Ch R = 1 ,1419.6  ,311.1,297.3,283.5
XS GIS Cut Line= 3
     2060934.508       309721.52     2061650.354      311151.549
     2061652.696      311843.471
#Sta/Elev= 30
     9.9 2064.93   208.6 2055.43   258.3 2051.64   337.7  2041.4   427.1 2036.36
   456.9 2036.61   536.4 2027.43   725.1 2013.55   764.8  2012.8   903.9 2002.88
   923.8 2003.67    1043 1997.75  1191.9 1987.53  1231.7 1987.66  1301.2 1980.64
  1390.6 1975.69    1480 1971.84  1509.8 1972.58  1609.1 1965.26  1648.6 1956.62
  1895.5 1948.27  1895.7 1948.26  1910.5 1949.77  1935.3 1959.42    1955 1963.06
  2004.5 1979.95  2123.1 1997.94  2202.2  2017.4    2212 2017.41  2291.1 2040.56
#Mann= 3 , 0 , 0
       0      .1       0  1895.5    .045       0  1910.5      .1       0
Bank Sta=1895.5,1910.5
XS Rating Curve= 0 ,0
Exp/Cntr=0.3,0.1

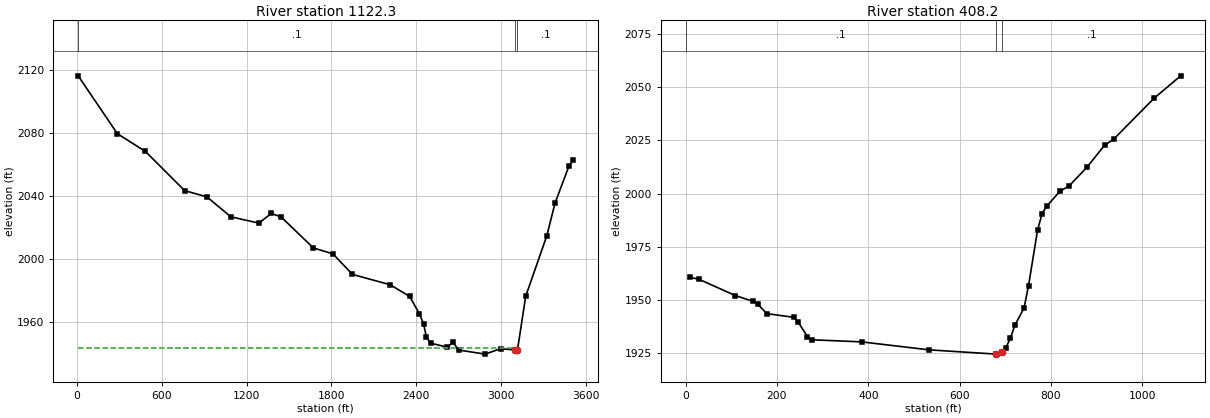
Type RM Length L Ch R = 1 ,1122.3  ,705.4,714.1,749.7
XS GIS Cut Line= 5
     2058688.822      311075.985     2059929.348      310735.176
     2060578.636      310865.995      2061045.63      311099.817
     2061644.947       311947.29
#Sta/Elev= 30
     9.9 2116.33     287 2079.53   484.9 2068.27     762 2043.36   920.3 2039.33
  1088.6 2026.68  1286.5 2022.69  1375.5  2028.8  1444.7 2026.57    1672  2006.9
  1810.4  2003.1  1948.8 1990.05  2214.9 1983.49  2352.8 1976.03  2421.8 1965.02
  2451.4 1958.48  2471.1 1950.32  2500.7 1946.36  2619.4 1943.73  2658.9 1946.97
  2698.5 1941.98  2886.3 1939.36    2995 1942.82    3100 1941.99    3115  1942.1
    3173 1976.18  3321.2 2014.33  3380.5 2035.42  3479.4 2059.12  3509.1 2062.67
#Mann= 3 , 0 , 0
     9.9      .1       0    3100    .045       0    3115      .1       0
#XS Ineff= 2 , 0
         3072.65 1943.14
Permanent Ineff=
       F       F
Bank Sta=3100,3115
XS Rating Curve= 0 ,0
Exp/Cntr=0.3,0.1

Type RM Length L Ch R = 1 ,408.2   ,416.7,408.2,399.8
XS GIS Cut Line= 3
     2060662.209      311237.717     2060797.826      312006.213
     2060965.087      312259.364
#Sta/Elev= 30
     9.9 1960.67    29.6 1959.76   108.7 1952.15   148.2 1949.39     158 1948.06
   177.8 1943.65   237.1 1941.92     247 1939.49   266.7 1932.91   276.6 1931.38
   385.2  1930.4   533.4 1926.65   678.5 1924.68   681.6 1924.65   693.5 1925.73
   701.3 1927.66   711.2 1932.26   721.1 1938.26   740.9 1946.31   750.7 1956.71
   770.5 1982.79   780.4 1990.56   790.2 1993.93   819.5  2001.1   839.1 2003.47
   878.2 2012.22   917.4  2022.7     937 2025.45  1025.1 2044.61  1083.8 2055.23
#Mann= 3 , 0 , 0
       0      .1       0   678.5    .045       0   693.5      .1       0
Bank Sta=678.5,693.5
XS Rating Curve= 0 ,0
Exp/Cntr=0.3,0.1

Chan Stop Cuts=-1
Use User Specified Reach Order=0